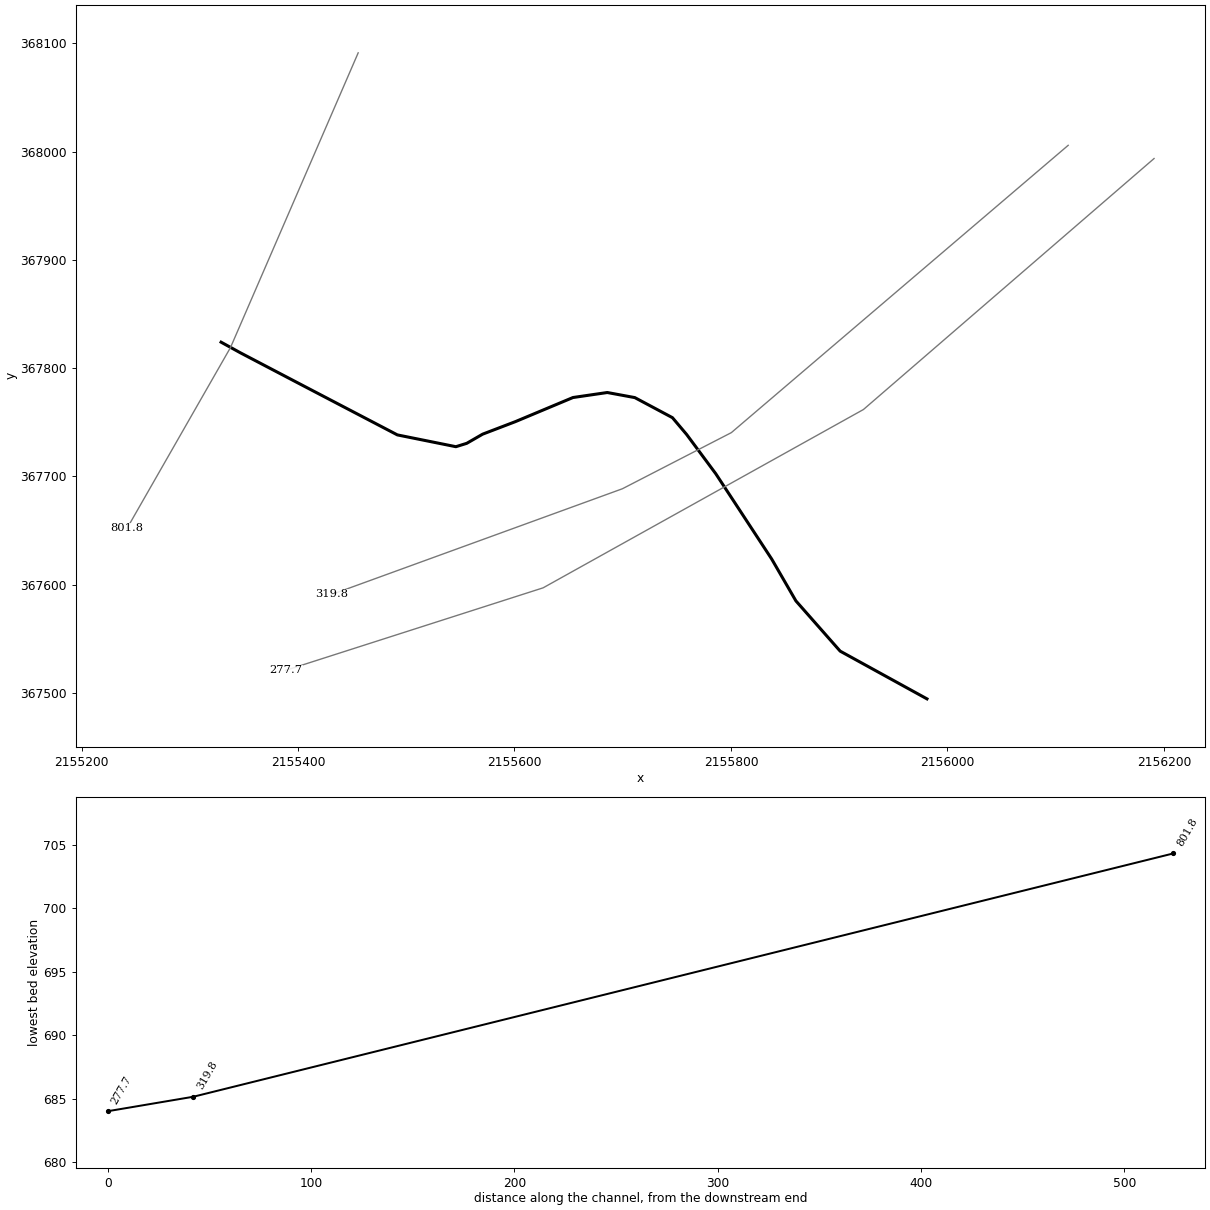
--- NP120.prj (project) ---

Proj Title=NP120
Current Plan=p01
Geom File=g01
Flow File=f01
Plan File=p01
DSS Export Rating Curves=0
DSS Export Rating Curve Sorted=0
DSS Export Volume Flow Curves=0
DXF OffsetX=0
DXF OffsetY=0
DXF ScaleX=0
DXF ScaleY=0

--- NP120.p01 (plan) ---

Plan Title=Floodplain
Program Version=4.00
Geom File=g01
Flow File=f01
K Sum by GR=0
Std Step Tol=0.01
Critical Tol=0.01
Num of Std Step Trials=20
Max Error Tol=0.3
Flow Tol Ratio=0.001
Split Flow NTrial=30
Split Flow Tol=0.02
Split Flow Ratio=0.02
Log Output Level=0
Friction Slope Method=1
Unsteady Friction Slope Method=2
Unsteady Bridges Friction Slope Method=1
Global Log Level=0
CheckData=False
Run HTab=0
Run UNet=0
Run PostProcess=0
UNET Theta=0
UNET Theta Warmup=0
UNET ZTol=0
UNET ZSATol=0
UNET MxIter=0
UNET MaxInSteps=0
UNET DtIC=0
UNET DtMin=0
UNET MaxCRTS=0
UNET WFStab=0
UNET SFStab=0
UNET WFX=0
UNET SFX=0
UNET DSS MLevel=0
UNET DZMax Abort=0
UNET Convert EG Bridges=0
UNET Use Existing IB Tables=0
UNET Froude Limit=0
UNET Froude Power=0
Write IC File=0
Echo Input=False
Echo Output=False
Write Detailed=0

--- NP120.f01 (steady flow) ---

Flow Title=NFF Regression Equation
Program Version=4.00
Number of Profiles=1
Profile Names=P100yr
River Rch & RM=NP120,Main      ,801.8
      35
River Rch & RM=NP120,Main      ,319.8
      38
River Rch & RM=NP120,Main      ,277.7
      40
Boundary for River Rch & Prof#=NP120,Main      ,1
Up Type=0
Dn Type=3
Dn Slope=0.033455

--- NP120.g01 (geometry) ---

Geom Title=USGS 10m DEM
Program Version=4.00

River Reach=NP120     ,Main
Reach XY= 19
     2155328.939      367823.932     2155346.759      367814.121
     2155399.988      367786.242     2155491.820      367738.253
     2155545.870      367727.356     2155555.922      367730.483
     2155570.617      367738.957     2155600.756      367750.476
     2155654.041      367772.790     2155685.745      367777.421
     2155711.180      367772.723     2155745.940      367754.174
     2155759.015      367738.700     2155786.008      367702.323
     2155803.756      367675.282     2155837.675      367623.509
     2155860.002      367584.900     2155900.882      367538.490
     2155981.099      367494.387

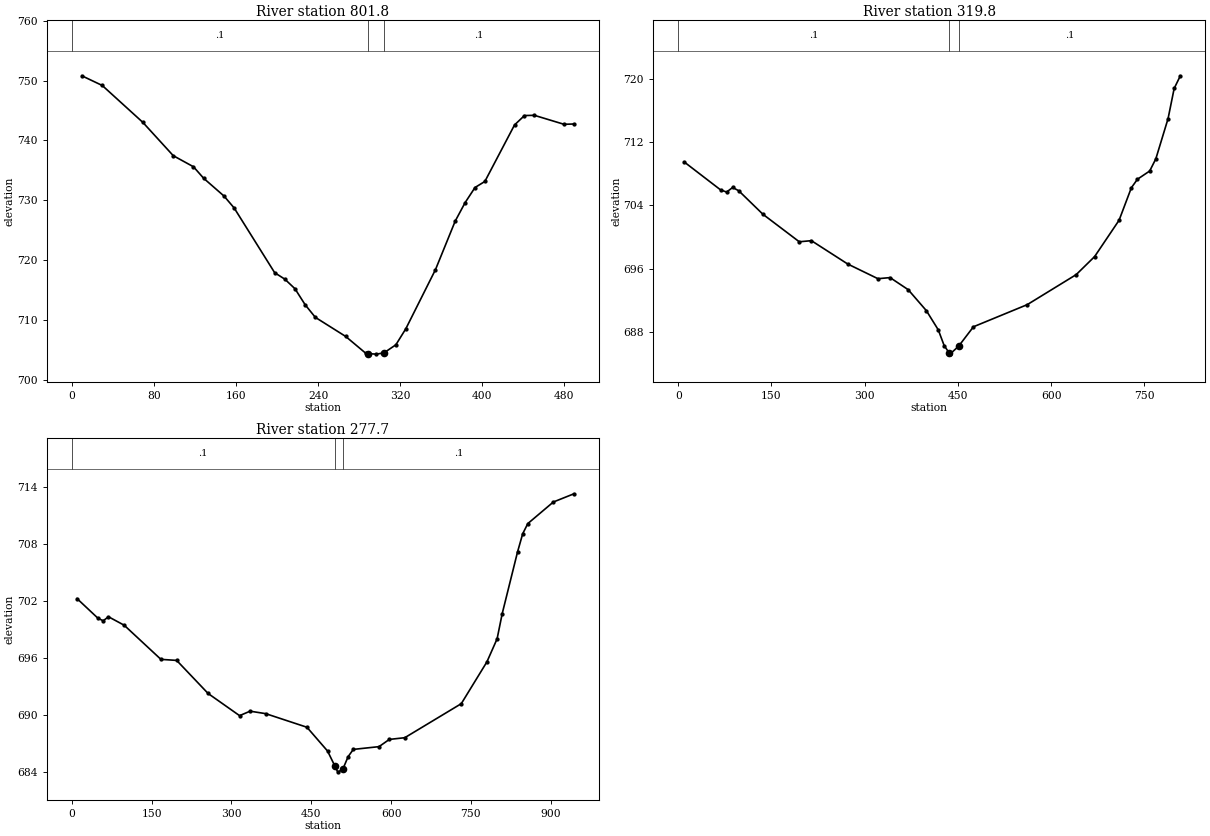
Type RM Length L Ch R = 1 ,801.8,497.4,482,469
XS GIS Cut Line= 3
     2155455.606      368091.233     2155337.699      367819.109
     2155242.034      367651.885
#Sta/Elev= 30
     9.9  750.78    29.7  749.17    69.2  743.02    98.9  737.45   118.6  735.60
   128.5  733.68   148.3  730.72   158.2  728.73   197.7  717.92   207.6  716.84
   217.5  715.24   227.4  712.57   237.3  710.47   266.9  707.28   286.7  704.44
   289.1  704.41   296.6  704.33   304.1  704.53   315.8  705.89   325.5  708.57
   354.4  718.44   373.6  726.53   383.3  729.63   392.9  732.14   402.5  733.15
   431.4  742.58   441.1  744.15   450.7  744.19   479.6  742.69   489.2  742.74
#Mann= 3 , 0 , 0
       0     0.1       0   289.1   0.045       0   304.1     0.1       0
Bank Sta=   289.1,   304.1
Exp/Cntr=0.3,0.1

Type RM Length L Ch R = 1 ,319.8,41.3,42.1,42.8
XS GIS Cut Line= 4
     2156111.577      368005.804     2155800.372      367740.364
     2155699.688      367688.497     2155431.197      367590.864
#Sta/Elev= 30
     9.7  709.47    68.2  705.94    77.9  705.67    87.6  706.25    97.4  705.83
   136.3  702.86   194.8  699.38   214.3  699.52   272.7  696.57   321.4  694.71
   340.9  694.85   370.1  693.32   399.3  690.67   418.5  688.24   427.9  686.26
   436.2  685.30   437.3  685.17   451.2  686.17   475.1  688.63   561.7  691.43
   640.5  695.23   670.1  697.51   709.5  702.11   729.2  706.21   739.0  707.29
   758.7  708.33   768.6  709.87   788.3  714.96   798.1  718.77   808.0  720.37
#Mann= 3 , 0 , 0
       0     0.1       0   436.2   0.045       0   451.2     0.1       0
Bank Sta=   436.2,   451.2
Exp/Cntr=0.3,0.1

Type RM Length L Ch R = 1 ,277.7,265,277.7,290.4
XS GIS Cut Line= 4
     2156190.903      367993.600     2155922.413      367761.722
     2155626.463      367596.966     2155388.483      367520.690
#Sta/Elev= 30
     9.9  702.28    49.3  700.21    59.1  699.95    69.0  700.37    98.5  699.48
   167.5  695.89   197.1  695.78   256.2  692.30   315.3  689.97   335.1  690.44
   364.4  690.18   441.9  688.75   480.6  686.25   494.3  684.68   499.9  684.03
   509.3  684.34   519.3  685.66   529.0  686.42   577.3  686.71   596.7  687.47
   625.7  687.65   731.9  691.23   780.0  695.62   799.2  698.05   808.8  700.70
   837.7  707.21   847.3  709.10   856.9  710.17   904.9  712.44   943.4  713.30
#Mann= 3 , 0 , 0
       0     0.1       0   494.3   0.045       0   509.3     0.1       0
Bank Sta=   494.3,   509.3
Exp/Cntr=0.3,0.1